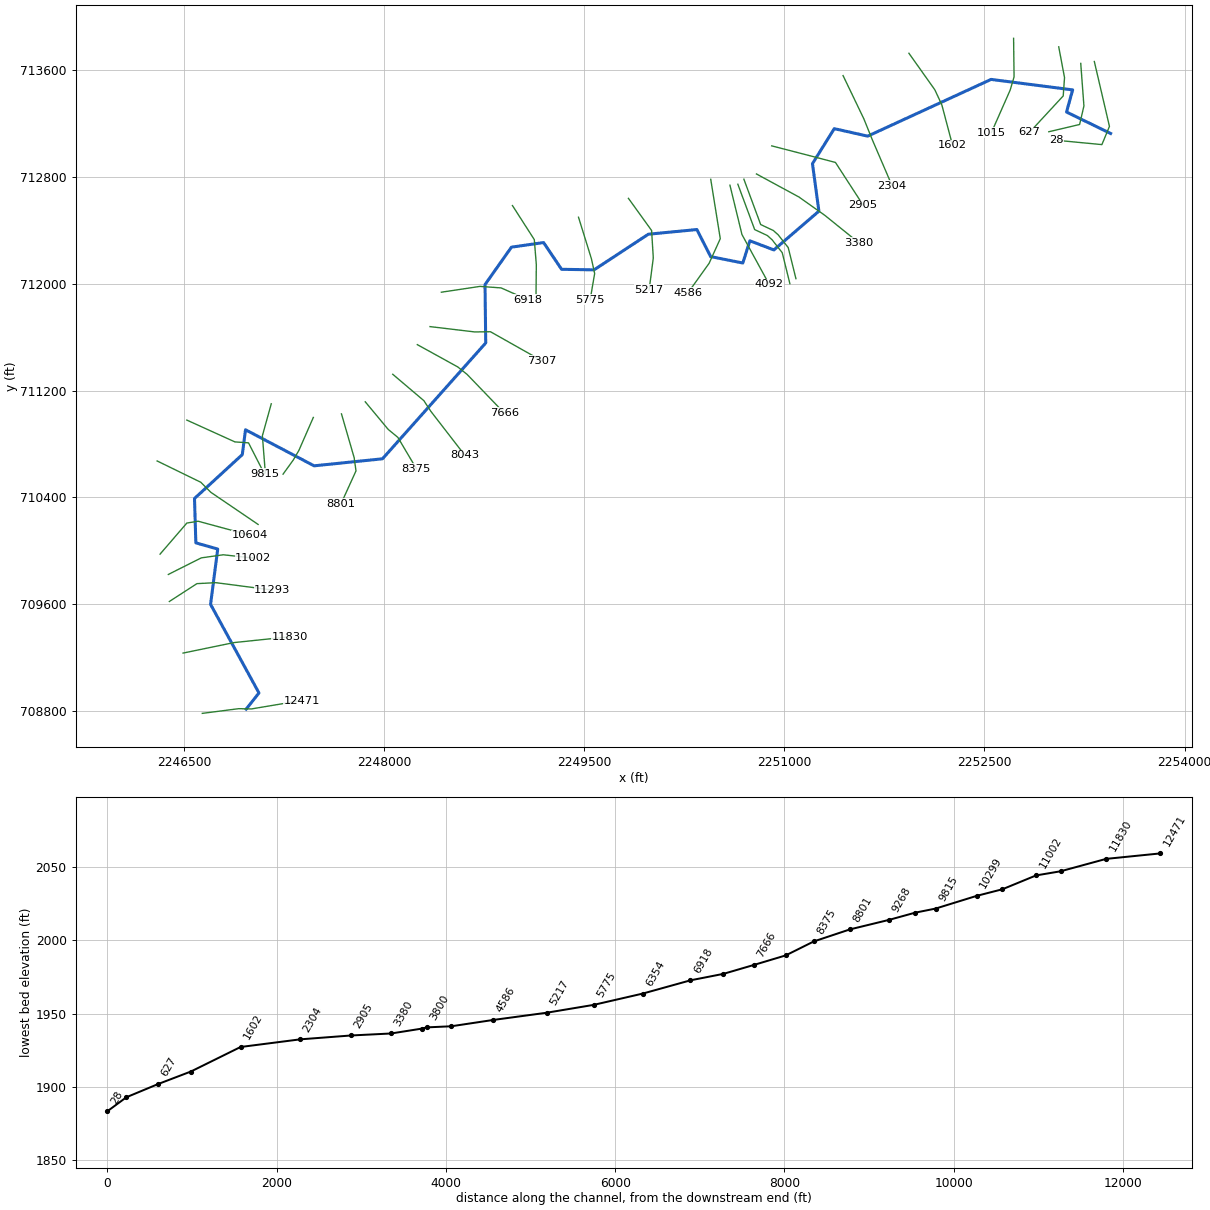
--- LILLAUREL.prj (project) ---

Proj Title=LILLAUREL
Current Plan=p01
Default Exp/Contr=0,0
English Units
Geom File=g01
Flow File=f01
Plan File=p01
BEGIN DESCRIPTION:
----------MODEL BY WOOD PLC 2022----------
AFH study
Randolph County, WV
HEC-RAS Version: RAS 6.2
Vertical Datum: NAVD88
Projection: NAD 1983 StatePlane West Virginia S FIPS 4702 (US Feet)
Terrain: 1-meter LIDAR (FEMA Region III 3DEP collected 2016-2018)
Land Use: 2019 NLCD
Hydrologic Method:
WV SIR2010-5033 regression equations
Additional Model Notes:
None
END DESCRIPTION:
DSS Export Rating Curves= 0
DSS Export Rating Curve Sorted= 0
DSS Export Volume Flow Curves= 0
DXF OffsetX= 0
DXF OffsetY= 0
DXF ScaleX= 0
DXF ScaleY= 0

--- LILLAUREL.p01 (plan) ---

Plan Title=Floodplain
Program Version=6.20
Short Identifier=Floodplain
Geom File=g01
Flow File=f01
Subcritical Flow
K Sum by GR= 0
Std Step Tol= 0.01
Critical Tol= 0.01
Num of Std Step Trials= 20
Max Error Tol= 0.3
Flow Tol Ratio= 0.001
Split Flow NTrial= 30
Split Flow Tol= 0.02
Split Flow Ratio= 0.02
Log Output Level= 0
Friction Slope Method= 1
Unsteady Friction Slope Method= 2
Unsteady Bridges Friction Slope Method= 1
Parabolic Critical Depth
Global Vel Dist= 0 , 0 , 0
Global Log Level= 0
CheckData=True
Encroach Param=-1 ,0,0, 0
Mapping Interval=1HOUR
Computation Time Step Use Courant=        0
Computation Time Step Use Time Series=    0
Computation Time Step Count To Double=0
Computation Time Step Max Doubling=0
Computation Time Step Max Halving=0
Computation Time Step Residence Courant=0
Run HTab= 0
Run UNet= 0
Run Sediment= 0
Run PostProcess= 0
Run WQNet= 0
Run RASMapper=-1
UNET Theta= 0
UNET Theta Warmup= 0
UNET ZTol= 0
UNET ZSATol= 0
UNET MxIter= 0
UNET Max Iter WO Improvement= 0
UNET MaxInSteps= 0
UNET DtIC= 0
UNET DtMin= 0
UNET MaxCRTS= 0
UNET WFStab= 0
UNET SFStab= 0
UNET WFX= 1
UNET SFX= 1
UNET Gravity=32.174
UNET 1D Methodology=Finite Difference
UNET DSS MLevel= 1
UNET Pardiso=0
UNET DZMax Abort= 0
UNET Use Existing IB Tables= 0
UNET Froude Reduction=False
UNET Froude Limit= 0
UNET Froude Power= 0
UNET D1 Cores= 0
UNET WindReference=Eulerian
UNET WindDragFormulation=Hsu (1988)
UNET D2 Coriolis=0
UNET D2 Cores= 0
UNET D2 Theta= 1
UNET D2 Theta Warmup= 1
UNET D2 Z Tol= 0.01
UNET D2 Volume Tol= 0.01
UNET D2 Max Iterations= 20
UNET D2 Equation= 0
UNET D2 RampUpFraction=0.1
UNET D2 TimeSlices= 1
UNET D2 Turbulence Formulation=Non-Conservative (original)
UNET D2 Eddy Viscosity=0.3
UNET D2 Transverse Eddy Viscosity=0.1
UNET D2 Smagorinsky Mixing=0
UNET D2 BCVolumeCheck=0
UNET D2 Cores=0
UNET D2 SolverType=PARDISO (Direct)
UNET D2 Minimum Iterations= 2147483647
UNET D2 Maximum Iterations= 2147483647
UNET D2 Restart Number= 10
UNET D2 Relaxation Coeff=1.3
UNET D2 SOR Precondition Iterations= 10
UNET D2 ILUT Maximum Fill= 8
UNET D2 ILUT Tolerance=1E-08
UNET D1D2 MaxIter= 0
UNET D1D2 ZTol=0.01
UNET D1D2 QTol=0.1
UNET D1D2 MinQTol=1
Write IC File= 0
Write IC File at Fixed DateTime=0
Write IC File at Sim End=0
Echo Input=False
Echo Parameters=False
Echo Output=False
Write Detailed= 0
HDF Write Warmup=0
HDF Write Time Slices=0
HDF Flush=0
HDF Compression= 1
HDF Chunk Size= 1
HDF Spatial Parts= 1
HDF Use Max Rows=0
HDF Fixed Rows= 1
Calibration Method= 0
Calibration Iterations= 20
Calibration Max Change=0.05
Calibration Tolerance=0.2
Calibration Maximum=1.5
Calibration Minimum=0.5
Calibration Optimization Method= 1
WQ AD Non Conservative
WQ ULTIMATE=-1
WQ Max Comp Step=1HOUR
WQ Output Interval=15MIN
WQ Output Selected Increments= 0
WQ Output face flow=0
WQ Output face velocity=0
WQ Output face area=0
WQ Output face dispersion=0
WQ Output cell volume=0
WQ Output cell surface area=0
WQ Output cell continuity=0
WQ Output cumulative cell continuity=0
WQ Output face conc=0
WQ Output face dconc_dx=0
WQ Output face courant=0
WQ Output face peclet=0
WQ Output face adv mass=0
WQ Output face disp mass=0
WQ Output cell mass=0
WQ Output cell source sink temp=0
WQ Output nsm pathways=0
WQ Output nsm derived pathways=0
WQ Create Restart=0
WQ Fixed Restart=0
WQ System Summary=0
WQ Write To DSS=0
Sorting and Armoring Iterations= 10
XS Update Threshold= 0.02
Bed Roughness Predictor= 0
Hydraulics Update Threshold= 0.02
Energy Slope Method= 1
Volume Change Method= 1
Sediment Retention Method= 0
Sediment TS Multiplier= 1
Warm Up Method= 0
XS Weighting Method= 0
Number of US Weighted Cross Sections= 1
Number of DS Weighted Cross Sections= 1
Upstream XS Weight=0
Main XS Weight=1
Downstream XS Weight=0
Number of DS XS's Weighted with US Boundary= 1
Upstream Boundary Weight= 1
Weight of XSs Associated with US Boundary= 0
Number of US XS's Weighted with DS Boundary= 1
Downstream Boundary Weight= 0.5
Weight of XSs Associated with DS Boundary= 0.5
Percentile Method= 0
Sediment Output Level= 3
Mass or Volume Output= 0
Output Increment Type= 1
Profile and TS Output Increment= 1
Transport Output Increment 1
XS Output Flag= 0
XS Output Increment= 10
Read HDF5 Sediment Hotstart= 0
Sediment Hotstart Type= 0
Write Gradation File= 0
Read Gradation Hotstart= 0
Write HDF5 File= 1
Write Binary Output= 1
Write DSS Sediment File= 0
DSS Sediment Output Type= 1
SV Curve= 0
Specific Gage Flag= 0
Subcell Erosion Methods= 0
Subcell Deposition Methods= 0
Advection Scheme= 1
Matrix Solver= 0
Implicit Weighting Factor= 1
Maximum Outer Loop Convergence Iterations= 5
Convergence Maximum Absolute= 0.001
Convergence RMSE= 0.0001
Grain Fractions Max Abs Error= 0.001
Max Subgrid Regions= 1
Max Subgrid Length Scale= 3.402823E+38
Initial Layer Thickness= 3.402823E+38
Min Layer Thickness= 3.402823E+38
Max Layer Thickness= 3.402823E+38
Number of Layers= 5

--- LILLAUREL.f01 (steady flow) ---

Flow Title=Flow
Program Version=6.20
Number of Profiles= 1
Profile Names=P100yr
River Rch & RM=LILLAUREL,Main,12471
     375
River Rch & RM=LILLAUREL,Main,9815
     429
River Rch & RM=LILLAUREL,Main,6354
     484
River Rch & RM=LILLAUREL,Main,4092
     561
Boundary for River Rch & Prof#=LILLAUREL,Main            , 1
Up Type= 0
Dn Type= 3
Dn Slope=0.03061
DSS Import GetInterval= 0
DSS Import GetPeak= 0
DSS Import FillOption= 0

--- LILLAUREL.g01 (geometry) ---

Geom Title=Geometry
Program Version=6.20

River Reach=LILLAUREL       ,Main
Reach XY= 30
2246967.38489902708813.591253348     2247063.078      708934.953
     2246700.433      709598.668     2246753.992      710013.252
     2246590.103       710059.78     2246580.033      710392.236
     2246938.139      710720.962     2246962.354      710907.335
     2247476.388      710636.968     2247989.153       710689.75
     2248762.561      711557.939     2248757.237      711995.106
      2248955.32      712275.724      2249196.43      712310.214
     2249330.728      712109.867     2249574.478        712105.7
     2249981.367      712372.905     2250345.043      712407.783
     2250448.206      712205.051     2250689.225      712157.076
     2250742.191      712323.314       2250922.1      712255.115
     2251259.599      712545.504     2251211.277      712901.532
     2251374.706      713163.894     2251625.306      713107.803
     2252549.709      713532.969     2253161.172      713454.422
     2253115.327      713288.361     2253445.431       713127.84

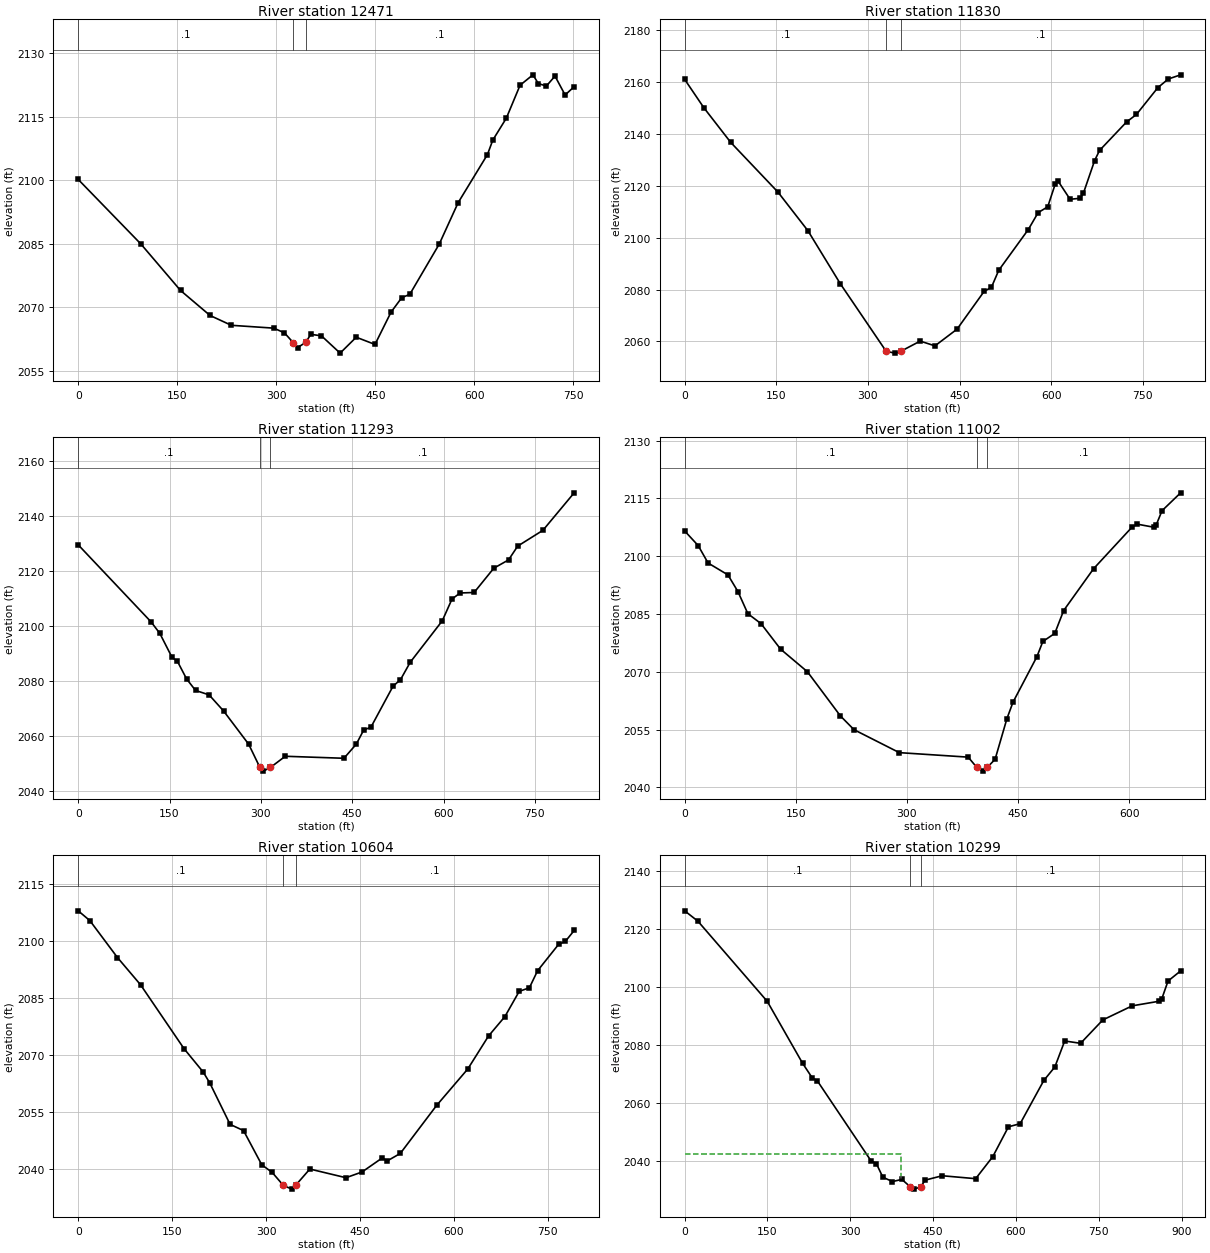
Type RM Length L Ch R = 1 ,12471   ,637.2,640.8,635.1
XS GIS Cut Line= 4
2246638.19087574708781.7777425962246911.54610526708816.989710621
2247005.91634441708815.0146847142247381.67059469708877.974457114
#Sta/Elev= 30
       0 2100.19    94.8 2084.99   154.9 2074.02   199.6 2068.12   231.9  2065.8
   296.2 2065.13   312.3 2064.01   325.5 2061.74   332.3 2060.56   344.3 2061.75
   352.3 2063.67   368.3 2063.32   396.6 2059.24     421 2062.99   449.4 2061.29
   473.7  2068.9   489.9 2072.31   502.1  2073.1   546.7 2084.95   575.3 2094.71
   619.7 2106.06   627.8 2109.47   648.3 2114.64   669.1 2122.41   688.6 2124.86
   696.8  2122.8   708.9 2122.21     722 2124.56   737.3 2120.11     751 2122.06
#Mann= 3 ,-1,0
       0      .1       0   325.5    .045       0   344.3      .1       0
Bank Sta=325.5,344.3
XS Rating Curve= 0 ,0
Exp/Cntr=0.3,0.1

Type RM Length L Ch R = 1 ,11830   ,538.8,537.2,537.2
XS GIS Cut Line= 4
2246494.51279584 709233.706044382246802.31941716709297.201819531
2246877.94684684 709312.585954282247296.18638758 709356.10431066
#Sta/Elev= 30
       0 2160.87    31.4 2149.96    75.4 2136.62   152.8 2117.47   201.8 2102.62
   254.9 2082.19  330.012056.168   344.8 2055.51  353.472056.169   385.6 2060.14
   409.8 2058.31     446 2064.75   490.2 2079.25   502.3 2080.88   514.2 2087.39
   562.6 2103.08   578.7 2109.59   594.4 2111.83   606.8 2120.66   610.9  2121.9
     631 2114.73   647.1  2115.1   652.7 2116.98   671.2 2129.62   679.2 2133.51
   723.5 2144.49   739.6 2147.36   774.8 2157.72   791.8 2161.02     812 2162.63
#Mann= 3 ,-1,0
       0      .1       0  330.01    .045       0  353.47      .1       0
Bank Sta=330.01,353.47
XS Rating Curve= 0 ,0
Exp/Cntr=0.3,0.1

Type RM Length L Ch R = 1 ,11293   ,289,290.9,289.8
XS GIS Cut Line= 4
2246391.70691668709620.4388840542246598.28338196709754.092134836
2246740.85585498 709761.248601642247163.07494203709706.212152172
#Sta/Elev= 30
       0 2129.47   119.7 2101.41     134 2097.24   154.2 2088.45   162.9 2087.07
   178.1 2080.61   192.8 2076.44   214.9 2074.85   238.8 2068.97     280 2056.87
  298.462048.397     304 2047.07  315.662048.395   340.1 2052.48   436.5 2051.75
   456.7 2056.88   468.8 2061.99   480.9 2063.11   517.2 2078.03   529.3 2080.35
   545.4 2086.73   597.9 2101.78     614 2109.75   627.3 2111.94   650.3 2112.12
   682.6 2120.96   706.8 2123.98   721.9 2129.01   763.3 2134.76   814.6 2148.41
#Mann= 3 ,-1,0
       0      .1       0  298.46    .045       0  315.66      .1       0
Bank Sta=298.46,315.66
XS Rating Curve= 0 ,0
Exp/Cntr=0.3,0.1

Type RM Length L Ch R = 1 ,11002   ,394.3,397.5,391.3
XS GIS Cut Line= 4
2246383.94125041709822.9962210172246631.01828304709947.257184794
2246795.73630479709970.375503636 2247021.1399135709945.812289866
#Sta/Elev= 30
       0 2106.57    18.2 2102.78    31.6 2098.25    58.4 2095.17    71.9 2090.84
    85.3  2085.1   103.1 2082.51   129.5 2075.89   165.7 2070.03   210.3 2058.55
   228.6 2054.99   289.8 2049.03   382.8 2047.86  394.212045.242   402.9 2044.23
  408.742045.242   419.1  2047.3   435.1 2057.86   443.3 2062.13   475.5 2073.91
   483.6 2077.89   499.7 2079.98   511.7 2085.92     552 2096.75   604.3 2107.63
   611.3 2108.33   633.1 2107.55   636.5 2108.07   644.5 2111.83   669.6 2116.47
#Mann= 3 ,-1,0
       0      .1       0  394.21    .045       0  408.74      .1       0
Bank Sta=394.21,408.74
XS Rating Curve= 0 ,0
Exp/Cntr(USF)=0,0
Exp/Cntr=0.3,0.1

Type RM Length L Ch R = 1 ,10604   ,312,305.1,293.5
XS GIS Cut Line= 4
2246321.81720511709975.080864899 2246522.6653115710208.110186647
2246607.34071905710221.9320729312246992.19735218710117.522465268
#Sta/Elev= 30
       0 2107.94    18.6 2105.37    62.7 2095.66    99.6  2088.5     169 2071.72
   199.7 2065.56   210.2 2062.69   242.6 2051.82   264.1 2050.18   293.2  2041.2
   309.9 2039.18  327.692035.776   341.2  2034.8  347.182035.778     370 2040.08
   427.7  2037.8   453.4 2039.31   485.5 2042.98   493.8 2042.23   514.5 2044.18
   572.5  2056.8   622.3 2066.38   655.5 2075.06   681.6 2080.15   704.4 2086.77
   720.7 2087.72   733.8  2092.2   767.3 2099.11   778.2 2099.92   792.2 2102.77
#Mann= 3 ,-1,0
       0      .1       0  327.69    .045       0  347.18      .1       0
Bank Sta=327.69,347.18
XS Rating Curve= 0 ,0
Exp/Cntr(USF)=0,0
Exp/Cntr=0.3,0.1

Type RM Length L Ch R = 1 ,10299   ,480.8,484,492.2
XS GIS Cut Line= 4
2246300.27805537710673.3645830522246627.36898028 710513.68985749
2246702.71928733710438.3807114712247056.61364633710197.924424858
#Sta/Elev= 30
       0 2126.17      24 2122.59   149.6 2094.97   213.5 2073.67   231.3 2068.54
   240.2 2067.62     338  2039.9   347.1 2039.11     359 2034.39   376.4 2032.88
   393.4 2033.63  408.562031.104     416 2030.28  427.732031.103   435.6 2033.38
   466.6 2034.89   527.1 2033.88   558.1 2041.46   586.5 2051.76   607.7 2052.82
   650.6 2067.73   670.6 2072.38   688.4 2081.33   717.2 2080.52   757.5 2088.58
   810.8 2093.44   859.2 2095.01     864 2095.68   875.6 2101.98   898.4 2105.47
#Mann= 3 ,-1,0
       0      .1       0  408.56    .045       0  427.73      .1       0
#XS Ineff= 2 , 0
          392.02 2042.33
Permanent Ineff=
       F       F
Bank Sta=408.56,427.73
XS Rating Curve= 0 ,0
Exp/Cntr=0.3,0.1

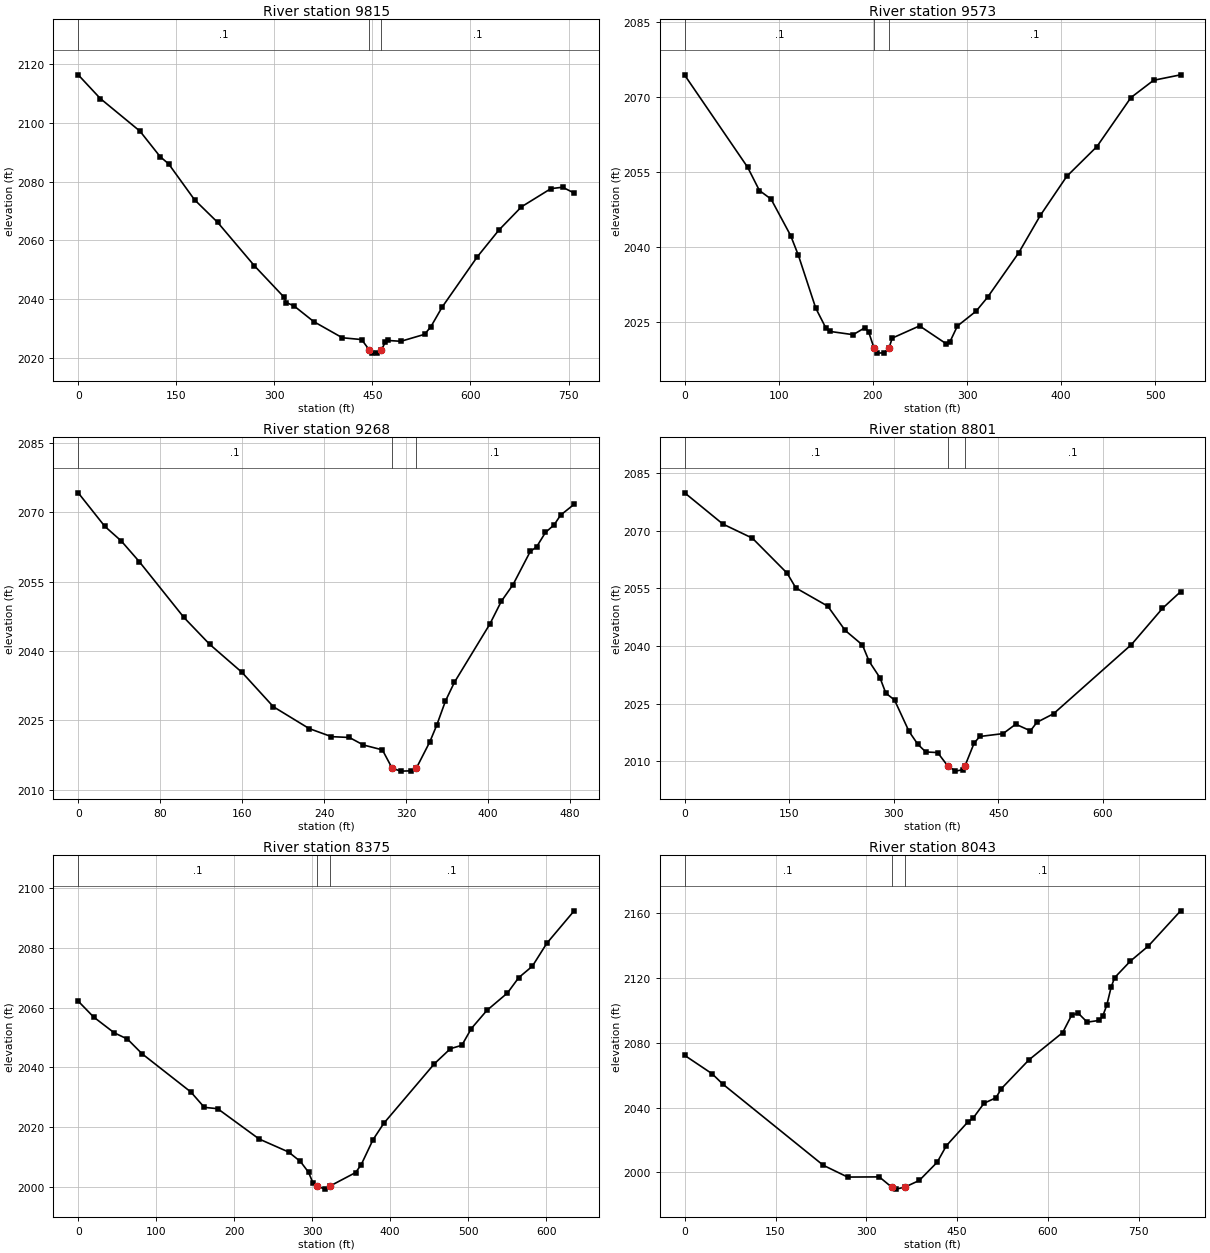
Type RM Length L Ch R = 1 ,9815    ,254.9,242.3,223.6
XS GIS Cut Line= 4
2246522.13612266710979.9424096642246882.79053982710816.362291317
2246984.75719236710809.239273621 2247103.3764256710577.491086447
#Sta/Elev= 30
       0 2116.39    33.8 2108.32    94.5  2097.2   125.2 2088.57   138.4 2086.04
   177.9 2073.86   213.1  2066.2   269.5 2051.38   314.1 2040.86   318.5 2038.84
     330 2037.73   360.2 2032.38     404 2026.87   433.5 2026.26   445.3  2022.7
   449.5 2021.73   457.6 2021.64  463.72 2022.69   469.6 2025.33   473.6 2025.95
   493.6 2025.67   529.8 2028.04   539.5 2030.66   556.7 2037.32   610.6 2054.48
   643.5 2063.54     678 2071.45     723 2077.64     741 2078.12   758.6 2076.14
#Mann= 3 ,0,0
       0      .1       0   445.3    .045       0  463.72      .1       0
Bank Sta=445.3,463.72
XS Rating Curve= 0 ,0
Exp/Cntr=0.3,0.1

Type RM Length L Ch R = 1 ,9573    ,308.7,304.9,306
XS GIS Cut Line= 3
2247155.24109979711101.6572554452247088.75911339710862.508214473
2247110.69959047710584.621256431
#Sta/Elev= 30
       0 2074.45    66.9 2056.02    79.4 2051.37    91.8 2049.65   112.6 2042.36
   120.9 2038.37   139.3 2027.83     150 2023.88   154.1 2023.19     179 2022.53
   191.5 2023.92   195.6 2023.02     201 2019.96   203.9 2018.84   212.2  2018.9
   217.3 2019.95   220.5 2021.84   249.6 2024.29   277.6 2020.75   281.7 2021.04
   289.8 2024.26   309.7 2027.24   321.8    2030   354.9 2038.89   377.9 2046.38
     406  2054.2   438.1 2060.17   474.2 2069.96   498.3 2073.42     527 2074.51
#Mann= 3 ,0,0
       0      .1       0     201    .045       0   217.3      .1       0
Bank Sta=201,217.3
XS Rating Curve= 0 ,0
Exp/Cntr(USF)=0,0
Exp/Cntr=0.3,0.1

Type RM Length L Ch R = 1 ,9268    ,457.5,466.4,473.7
XS GIS Cut Line= 4
 2247470.5660754710999.6986279882247362.56149904710752.772026715
2247320.10247285 710680.35257511 2247243.5912842710574.495330287
#Sta/Elev= 30
       0 2074.19    25.9 2066.95      42 2063.78    59.5 2059.33   103.2 2047.22
   128.3 2041.42   159.9 2035.34   190.5 2027.91   225.4 2023.19   247.2 2021.44
   264.7 2021.26   278.3 2019.64   296.9 2018.58  306.432014.606   314.8 2013.98
   324.7 2014.04  330.04 2014.61   343.2 2020.31   349.9 2023.88   358.5 2029.16
   367.2 2033.19   401.8 2045.79     413 2050.72   424.4 2054.31   441.3 2061.52
   447.4 2062.48   456.1 2065.62   464.5 2067.25   470.9 2069.37   484.1 2071.71
#Mann= 3 ,0,0
       0      .1       0  306.43    .045       0  330.04      .1       0
Bank Sta=306.43,330.04
XS Rating Curve= 0 ,0
Exp/Cntr=0.3,0.1

Type RM Length L Ch R = 1 ,8801    ,415.6,426.6,433.3
XS GIS Cut Line= 4
2247681.47600362711026.3973007192247776.37652536710699.007322466
 2247790.2834061710599.118842856 2247678.4209239710353.546492761
#Sta/Elev= 30
       0 2079.82    54.8  2071.7    97.1 2068.03     147 2058.92   159.5 2055.08
   205.3 2050.34   230.3 2044.03     255 2040.26   264.7 2035.98   280.3 2031.68
   288.6 2027.72   301.1 2025.93   321.9 2017.76   334.4 2014.44   345.9 2012.42
   362.9 2012.26  377.142008.865   388.4 2007.43   399.3  2007.8  402.362008.866
   415.4 2014.76   423.5 2016.44   456.9 2017.19     475 2019.64   496.1 2017.91
   505.4 2020.13   529.3 2022.36   641.1 2040.36   685.6 2049.77   711.6 2054.11
#Mann= 3 ,-1,0
       0      .1       0  377.14    .045       0  402.36      .1       0
Bank Sta=377.14,402.36
XS Rating Curve= 0 ,0
Exp/Cntr=0.3,0.1

Type RM Length L Ch R = 1 ,8375    ,333.4,331.4,328
XS GIS Cut Line= 4
2247859.84146752711116.5883931792248031.53399709710910.136026338
2248104.21365684710850.0963074092248243.22699783710615.061029109
#Sta/Elev= 30
       0 2062.14    19.7 2056.84    46.1 2051.55    63.1 2049.45    81.8 2044.54
   144.4 2031.74   161.7 2026.59   178.8 2026.14     232 2015.99   269.7 2011.65
   284.9 2008.47   295.3 2004.88   300.9 2001.36  306.66 2000.26     316 1999.22
  322.88 2000.26   355.7 2004.77   362.8 2007.38     378 2015.76   391.7 2021.21
   456.8 2041.22   477.3 2046.24   491.9 2047.36   504.1 2052.98     524 2059.04
   550.3 2064.85   564.9 2070.03   582.3 2073.83   600.9 2081.53   635.9 2092.37
#Mann= 3 ,-1,0
       0      .1       0  306.66    .045       0  322.88      .1       0
Bank Sta=306.66,322.88
XS Rating Curve= 0 ,0
Exp/Cntr(USF)=0,0
Exp/Cntr=0.3,0.1

Type RM Length L Ch R = 1 ,8043    ,374.3,377.2,381.3
XS GIS Cut Line= 4
2248065.63892577711323.2556269512248298.92986473711125.408338717
2248351.83218974711044.8580557482248606.75638828 710715.07940312
#Sta/Elev= 30
       0 2072.17    45.3 2060.84    62.9 2054.48   228.9 2004.42   269.1 1997.15
   321.4 1997.25  341.651991.016   349.2 1989.71  364.051991.017   387.5 1995.06
     417 2006.27   432.2 2016.47   467.6 2031.08   476.4 2033.49   494.4 2042.67
     514 2046.01   523.2 2051.72   568.7 2069.45   624.3 2086.22   639.5 2097.22
   650.4 2098.02   664.8 2092.65     685 2093.75   690.6 2096.53   697.1 2103.09
   704.5 2114.45   710.2 2120.12   735.9 2130.21   765.9 2139.62   819.1 2161.29
#Mann= 3 ,-1,0
       0      .1       0  341.65    .045       0  364.05      .1       0
Bank Sta=341.65,364.05
XS Rating Curve= 0 ,0
Exp/Cntr=0.3,0.1

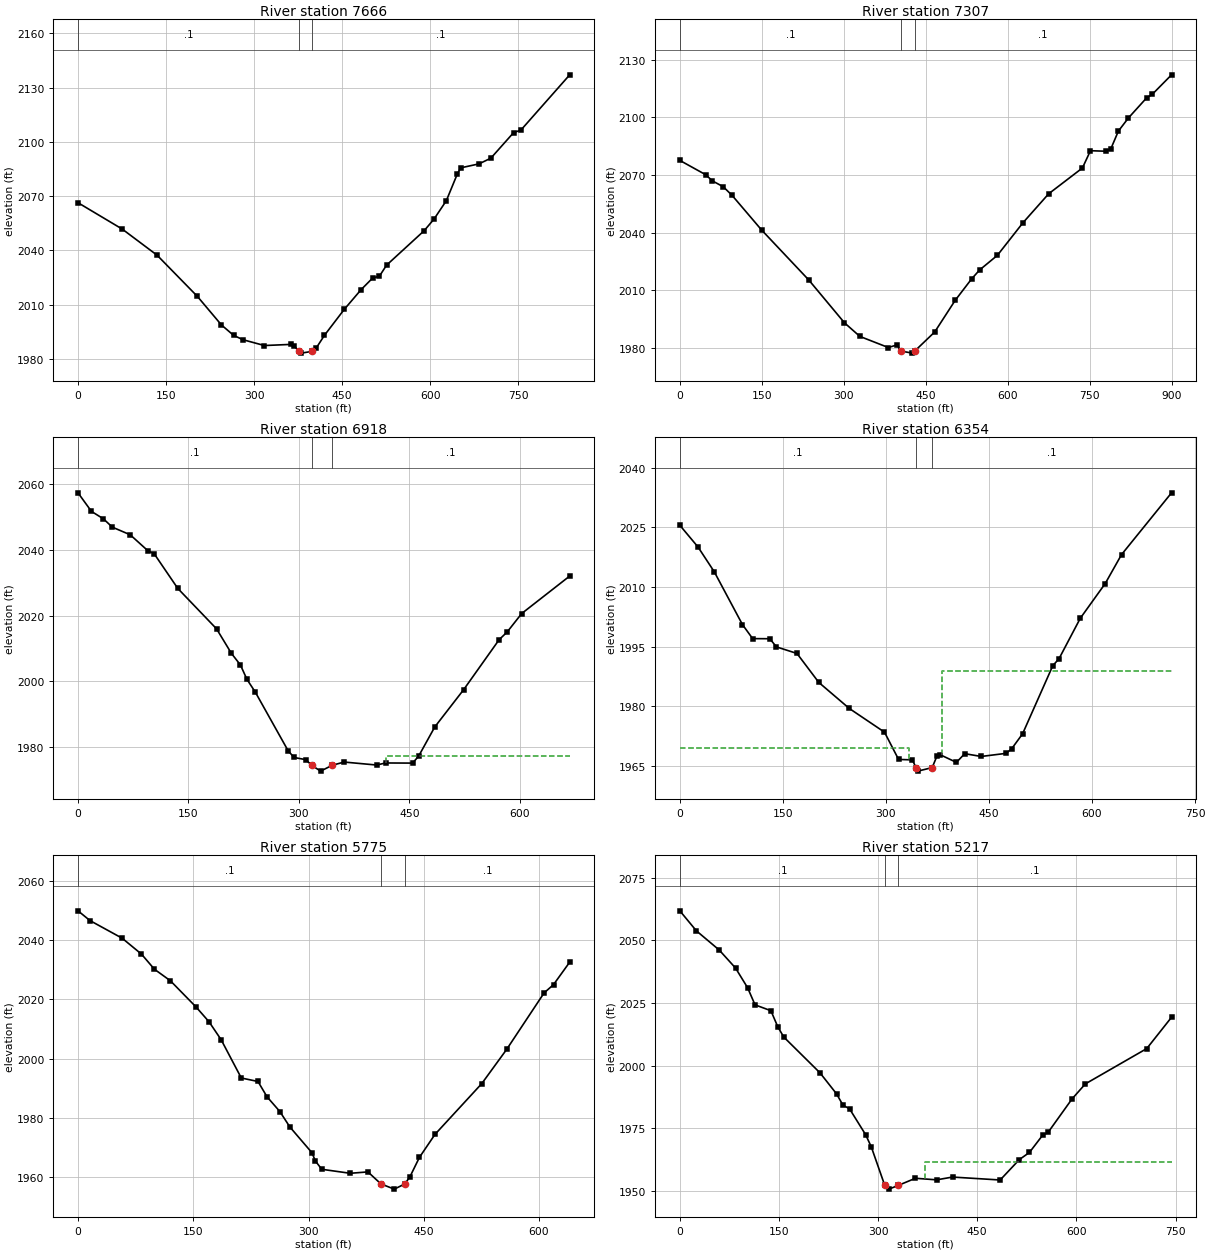
Type RM Length L Ch R = 1 ,7666    ,354,359.7,370.5
XS GIS Cut Line= 4
2248250.15871659711545.1227462912248552.74599831711378.287031491
2248623.37693041711321.8427179392248901.93277617711032.399880663
#Sta/Elev= 30
       0 2066.36    75.4 2051.77   134.8 2037.32   203.3 2014.58   244.4 1998.76
     265 1993.04   280.9 1990.62   317.5 1987.39     363 1988.02   368.7 1987.21
   375.81984.195   380.6 1983.19  399.191984.194   405.7 1985.94   419.9 1993.06
   453.5 2007.34   482.2 2018.26     502 2024.73   513.4 2025.69   525.7 2031.84
   589.7 2050.88   606.7 2057.39   627.5 2067.49   646.3 2082.32     652 2085.64
   683.1 2087.84   703.3 2090.98   742.2 2105.16   754.4 2106.48   837.7 2137.08
#Mann= 3 ,-1,0
       0      .1       0   375.8    .045       0  399.19      .1       0
Bank Sta=375.8,399.19
XS Rating Curve= 0 ,0
Exp/Cntr=0.3,0.1

Type RM Length L Ch R = 1 ,7307    ,387.7,388.2,384.2
XS GIS Cut Line= 4
2248345.23172034711680.4210790972248680.04198869711640.463988758
 2248798.1195915711641.9502612292249184.88077571 711423.81532712
#Sta/Elev= 30
       0 2077.59    47.3 2070.13    59.5 2066.93    79.5 2063.84    95.6 2059.36
   149.5 2041.33   235.9 2015.23   301.1 1992.93   329.3 1985.83   381.3 1980.04
   397.3 1981.41  404.211978.206   425.3 1977.12  429.68 1978.21   466.2 1988.16
   503.6 2004.63   533.7 2015.83   548.4  2020.5   580.7 2028.08   627.5 2045.06
   674.6 2060.19   736.3 2073.63     751 2082.64   779.1 2082.37   788.3 2083.63
   802.1 2092.88   820.4  2099.7   853.7 2110.18     864 2112.02   899.3  2122.2
#Mann= 3 ,-1,0
       0      .1       0  404.21    .045       0  429.68      .1       0
Bank Sta=404.21,429.68
XS Rating Curve= 0 ,0
Exp/Cntr=0.3,0.1

Type RM Length L Ch R = 1 ,6918    ,577.2,563.9,539.1
XS GIS Cut Line= 4
  2248430.062577711938.1665797492248719.56107247711981.706065951
2248877.71634508711970.450993007 2249075.7692663711882.751560123
#Sta/Elev= 30
       0 2057.31    18.3 2051.66    34.5 2049.41    46.6 2046.88    70.9 2044.56
    95.2 2039.65   103.3 2038.85   135.6 2028.24   188.2 2015.97   208.4 2008.51
   220.6    2005   229.5 2000.61   240.8 1996.76   285.3 1978.97   293.4 1976.88
   309.4 1976.22  317.34 1974.51   329.5 1972.73  345.341974.508   361.5 1975.49
   405.7 1974.58   417.7 1975.21   454.5 1975.17   462.7 1977.29   484.6 1986.15
   523.9 1997.51   572.1  2012.7   582.9 2015.01   602.7 2020.63   667.9 2032.02
#Mann= 3 ,-1,0
       0      .1       0  317.34    .045       0  345.34      .1       0
#XS Ineff= 2 , 0
                          417.78         1977.21
Permanent Ineff=
       F       F
Bank Sta=317.34,345.34
XS Rating Curve= 0 ,0
Exp/Cntr=0.3,0.1

Type RM Length L Ch R = 1 ,6354    ,569.6,579.3,577.1
XS GIS Cut Line= 4
 2248962.9148297712587.4649311532249126.61323078712332.424875736
2249141.76647884 712144.857831092249139.47302535711920.363137694
#Sta/Elev= 30
       0 2025.53    26.5 2020.06    50.2 2013.81    91.2 2000.54     106 1997.02
     131 1996.99   140.6 1994.94   170.5 1993.29   202.3    1986   246.7 1979.45
   297.9 1973.49   318.4 1966.63   338.4 1966.52  343.861964.575   346.4 1963.69
  367.281964.578   374.5 1967.57   378.5 1967.85   402.6 1965.89   414.7 1968.08
   438.7 1967.38   474.9 1968.16   482.9 1969.29   498.9 1973.08   542.9 1990.22
   551.9 1991.96   582.9 2002.14   619.2 2010.88   642.9 2018.15   715.7 2033.69
#Mann= 3 ,-1,0
       0      .1       0  343.86    .045       0  367.28      .1       0
#XS Ineff= 2 , 0
          334.17 1969.54  381.23         1988.99
Permanent Ineff=
       F       F
Bank Sta=343.86,367.28
XS Rating Curve= 0 ,0
Exp/Cntr=0.3,0.1

Type RM Length L Ch R = 1 ,5775    ,554.5,557.8,555
XS GIS Cut Line= 4
2249457.96059688712500.0900445442249554.76644715712188.521159071
2249578.90685207712078.4454763352249545.07970156711880.365865998
#Sta/Elev= 30
       0 2049.84    15.6 2046.55    57.5  2040.6    82.6 2035.24    99.4 2030.16
   120.3 2026.24   153.8 2017.37   170.6  2012.4   186.3 2006.37   212.5 1993.47
   234.2  1992.3     246 1987.13   262.7 1982.16   275.7 1976.96   304.5 1968.26
   308.8 1965.54   317.2 1962.69   354.3 1961.34   377.3 1961.81  394.261957.752
   411.6    1956  425.381957.754   432.1 1960.23   444.3  1966.7   464.6 1974.47
   525.5  1991.6   557.9 2003.14   606.6 2022.18   618.8 2024.95   639.9 2032.54
#Mann= 3 ,-1,0
       0      .1       0  394.26    .045       0  425.38      .1       0
Bank Sta=394.26,425.38
XS Rating Curve= 0 ,0
Exp/Cntr=0.3,0.1

Type RM Length L Ch R = 1 ,5217    ,633.5,631.3,622.8
XS GIS Cut Line= 4
2249832.20623189712641.5397826062250005.75360679 712400.65912366
2250018.35135023712194.1455699072249987.22167028711955.985543485
#Sta/Elev= 30
       0 2061.82    25.1 2053.82    59.6 2046.16    84.3 2038.96   102.6 2031.07
   113.8 2024.25   137.8 2021.91   148.3 2015.44   157.3 2011.39   212.1 1997.08
   237.1  1988.7   246.9 1984.16   256.8 1982.71   281.1 1972.39   289.7 1967.51
  310.04 1952.14   316.4 1950.62  330.781952.138   356.5 1954.96   388.5 1954.33
   412.6 1955.44   484.7 1954.27   513.7 1962.42     529 1965.28   549.1 1972.21
   557.2 1973.29   593.5 1986.68   613.6 1992.67   706.5 2006.78     744 2019.29
#Mann= 3 ,-1,0
       0      .1       0  310.04    .045       0  330.78      .1       0
#XS Ineff= 2 , 0
                          370.46         1961.61
Permanent Ineff=
       F       F
Bank Sta=310.04,330.78
XS Rating Curve= 0 ,0
Exp/Cntr=0.3,0.1

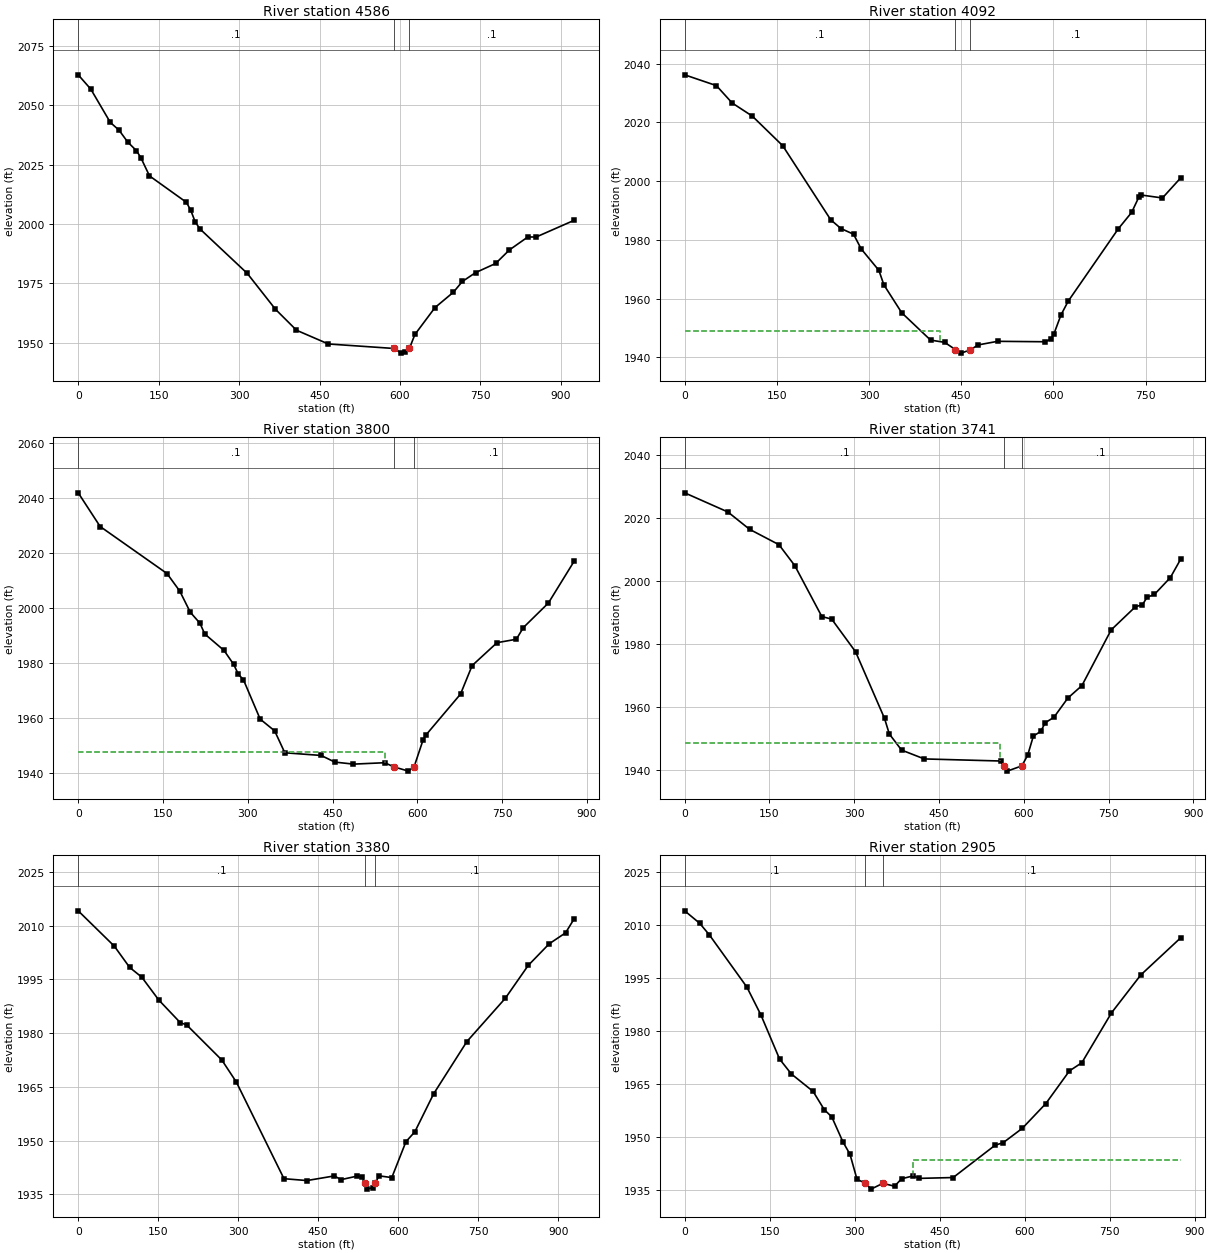
Type RM Length L Ch R = 1 ,4586    ,467.8,494,502.1
XS GIS Cut Line= 4
2250448.87798497712784.3543283222250520.42386355712339.276789081
2250436.82484154712154.9687997432250278.85826875711934.160612101
#Sta/Elev= 30
       0 2062.76    23.5 2056.73    59.9 2042.72    76.1 2039.49    92.3 2034.49
   108.6 2030.85   116.7 2027.95   132.9 2020.25   201.7 2009.14   209.8 2005.81
   217.9 2001.01   226.7    1998   315.2 1979.24   367.8 1964.14     407 1955.33
   466.3 1949.55  588.931947.657   602.4  1945.7   609.7    1946  617.521947.657
   627.8 1953.55   665.2 1964.85   699.6 1971.33   716.2 1975.83   740.9 1979.56
   778.3 1983.41     804 1989.11   838.4 1994.57   853.7 1994.53   924.7 2001.57
#Mann= 3 ,-1,0
       0      .1       0  588.93    .045       0  617.52      .1       0
Bank Sta=588.93,617.52
XS Rating Curve= 0 ,0
Exp/Cntr=0.3,0.1

Type RM Length L Ch R = 1 ,4092    ,275,292.1,296.9
XS GIS Cut Line= 3
2250592.80902729712740.1680908722250682.88710803712370.318088769
2250887.41733842711996.229118161
#Sta/Elev= 30
       0 2036.17    51.6  2032.5    77.2 2026.59   110.1  2022.1   159.5 2012.04
   237.7  1986.8   254.2 1983.84   274.8  1981.9   287.1 1976.93     316 1969.59
   324.2 1964.64   353.2 1955.15   400.1 1945.85     423 1945.08   440.6  1942.6
   450.1 1941.41     465 1942.56   477.7 1944.21   509.2 1945.43   587.1 1945.28
   596.2  1946.3   600.6 1947.83   612.3  1954.4   624.1 1959.11   705.6 1983.75
   727.3 1989.32   739.1 1994.57     742 1995.27   777.4 1994.24     807 2001.05
#Mann= 3 ,0,0
       0      .1       0   440.6    .045       0     465      .1       0
#XS Ineff= 2 , 0
          414.78 1948.81
Permanent Ineff=
       F       F
Bank Sta=440.6,465
XS Rating Curve= 0 ,0
Exp/Cntr(USF)=0,0
Exp/Cntr=0.3,0.1

Type RM Length L Ch R = 1 ,3800    ,59.4,59,58.8
XS GIS Cut Line= 6
2250652.25561708 712747.161519582250778.06650367 712407.56857445
2250872.80869626712363.046435678 2250908.5282673712331.314868439
2250984.57641927712234.6761428282251042.13484835712001.924616697
#Sta/Elev= 30
       0 2041.96    38.8  2029.7   157.1 2012.58   179.7 2006.19   198.3 1998.49
   215.4 1994.49   223.9 1990.58   258.1 1984.56   275.1  1979.5   283.6 1975.82
   292.2 1973.99     322 1959.57   347.6  1955.3   365.6 1947.32   429.8 1946.35
   454.1 1943.93   487.1 1943.19   542.4  1943.7  558.531942.198   584.4 1940.64
  594.331942.197     610 1951.85   614.9 1953.69   676.5 1968.68   697.1 1979.08
   741.1  1987.4   775.3 1988.65   787.7  1992.9     832 2001.84   877.6 2017.06
#Mann= 3 ,-1,0
       0      .1       0  558.53    .045       0  594.33      .1       0
#XS Ineff= 2 , 0
          542.38 1947.75
Permanent Ineff=
       F       F
Bank Sta=558.53,594.33
XS Rating Curve= 0 ,0
Exp/Cntr=0.3,0.1

Type RM Length L Ch R = 1 ,3741    ,358,360.9,363
XS GIS Cut Line= 6
2250697.44245596712784.7913028182250823.25334255712445.198357688
2250917.99553514712400.6762189162250953.71510618712368.944651677
2251029.76325815712272.3059260662251087.32168723712039.554399935
#Sta/Elev= 30
       0 2028.08    76.5    2022   114.8 2016.51   166.8 2011.63   194.8 2004.99
   242.7 1988.83   260.2    1988   302.4 1977.65   353.6 1956.53   362.1 1951.57
   383.8 1946.46     424 1943.65   559.1 1942.99  564.961941.449   570.8 1939.78
  596.691941.449     607 1944.86     617 1950.89   630.3 1952.42   637.8 1955.11
   653.4 1956.86   678.1 1962.97   702.9 1966.91   754.7 1984.59   797.6 1991.93
     810 1992.57   818.2 1994.92   831.2 1995.84   859.4 2001.18   877.6 2006.99
#Mann= 3 ,-1,0
       0      .1       0  564.96    .045       0  596.69      .1       0
#XS Ineff= 2 , 0
          558.22 1948.67
Permanent Ineff=
       F       F
Bank Sta=564.96,596.69
XS Rating Curve= 0 ,0
Exp/Cntr=0.3,0.1

Type RM Length L Ch R = 1 ,3380    ,469.2,475.3,473.1
XS GIS Cut Line= 4
2250791.43078711712824.3567779822251110.11868587712651.550679871
2251304.26674208 712513.995490872251560.66481339712307.155850695
#Sta/Elev= 30
       0  2014.1    67.8 2004.23    96.4 1998.33   119.2  1995.6     151 1989.24
   191.3 1982.93   203.5 1982.26   269.3 1972.49   296.6 1966.33   385.8  1939.4
   428.8 1938.88   480.5 1940.18   492.5 1939.12   521.9 1940.09   532.1 1939.93
   537.9 1938.12   541.5 1936.49   552.2 1936.93  557.151938.103   563.7  1940.2
     588 1939.71   614.5 1949.72   631.2 1952.48   666.4 1963.06   728.8 1977.65
   800.8 1989.71   843.8 1998.88     883 2004.89   913.8 2007.96   929.9 2011.87
#Mann= 3 ,-1,0
       0      .1       0   537.9    .045       0  557.15      .1       0
Bank Sta=537.9,557.15
XS Rating Curve= 0 ,0
Exp/Cntr=0.3,0.1

Type RM Length L Ch R = 1 ,2905    ,609.7,600.3,581.4
XS GIS Cut Line= 4
 2250905.9197859713034.9129993142251191.94034499712961.023930388
2251383.63996597712910.6242987422251590.79369528712590.932399889
#Sta/Elev= 30
       0 2014.12    26.3 2010.61    43.6 2007.28   109.7 1992.47   134.5 1984.54
   167.4 1972.03   188.2  1967.8   226.5 1962.85   246.2 1957.67   259.4 1955.63
   279.1 1948.52   291.5 1945.03   303.9  1937.9   318.4 1936.84   328.7 1935.12
   349.4 1936.76   370.1 1935.95   382.5 1938.05   403.2  1938.9   413.4 1938.17
   473.5 1938.41   547.1 1947.54   562.1 1948.35   595.4 1952.38   636.8 1959.39
   678.5 1968.68   700.4    1971   752.7 1985.16   804.5 1995.94   874.6 2006.44
#Mann= 3 ,-1,0
       0      .1       0   318.4    .045       0   349.4      .1       0
#XS Ineff= 2 , 0
                          403.34         1943.43
Permanent Ineff=
       F       F
Bank Sta=318.4,349.4
XS Rating Curve= 0 ,0
Exp/Cntr=0.3,0.1

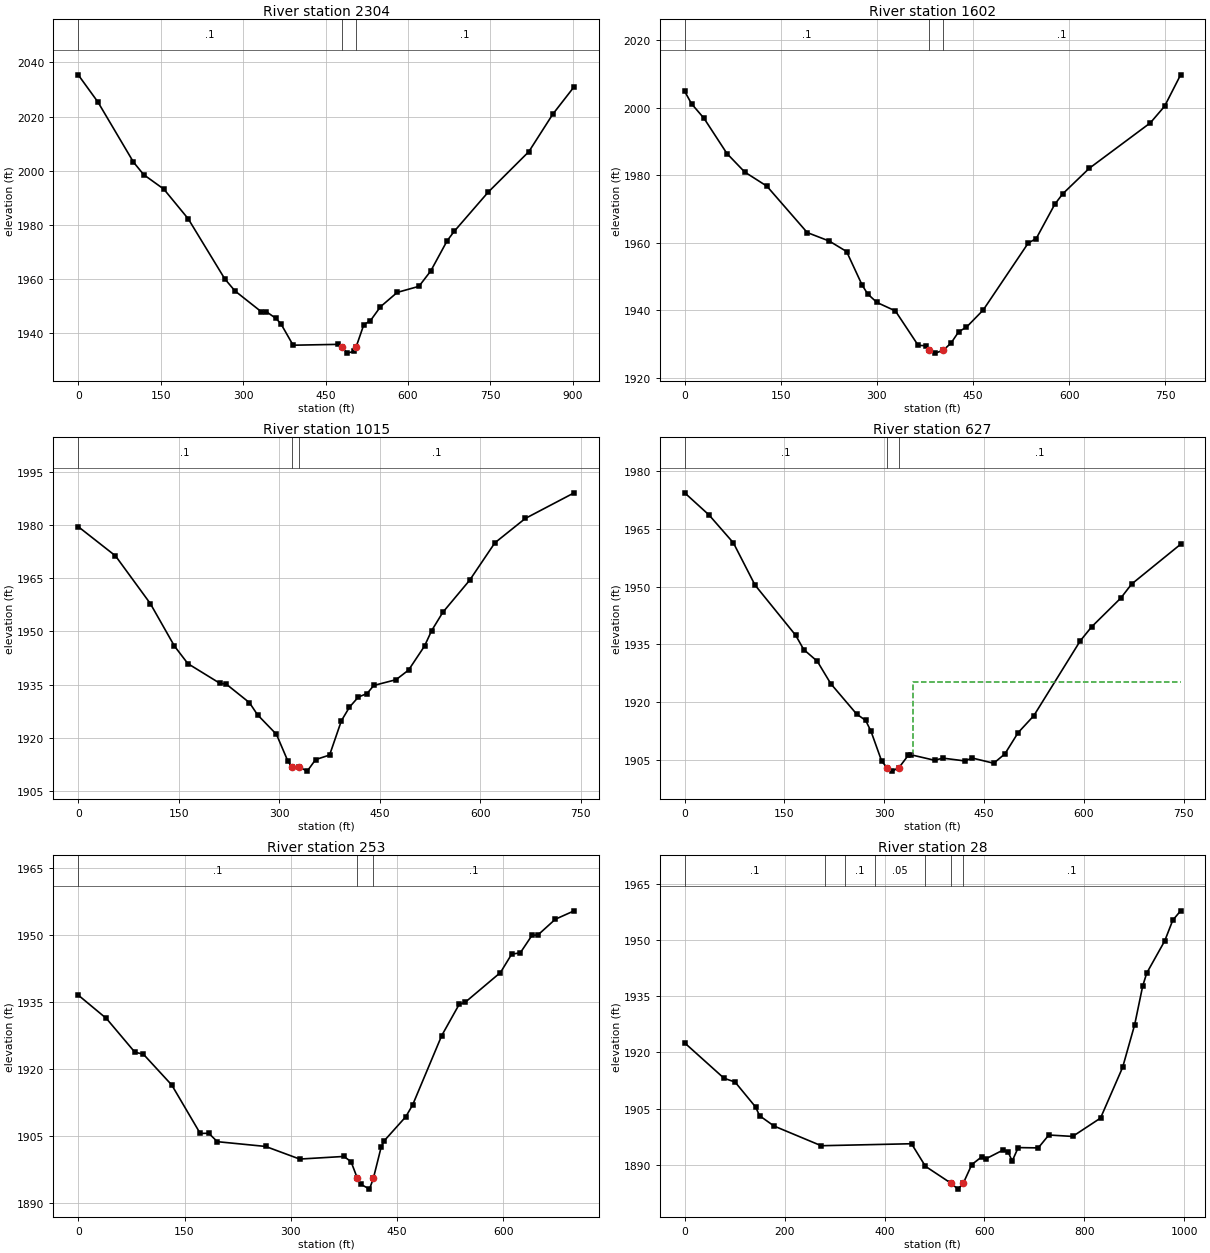
Type RM Length L Ch R = 1 ,2304    ,696.5,702.5,692.9
XS GIS Cut Line= 4
2251440.62516407 713561.561268562251596.35597733713237.488125604
2251660.52192899 713079.096177522251807.40562676      712737.487
#Sta/Elev= 30
       0 2035.43    35.9 2025.35   100.5 2003.15     119 1998.52   155.8 1993.14
   200.1 1982.18   266.7 1959.93   285.2 1955.49   333.3 1947.76   342.1 1947.83
   359.9 1945.31   368.9 1943.29     391 1935.41   472.1 1935.72  479.371934.867
   489.4 1932.48   500.9 1933.11  505.781934.868   519.6 1943.01   531.6 1944.47
   549.9 1949.63   580.4 1954.94   619.9 1957.19   641.4 1962.87   671.3 1974.07
   683.9 1977.48   745.9 1992.03   819.9 2007.02   863.4 2020.86   902.3 2031.03
#Mann= 3 ,-1,0
       0      .1       0  479.37    .045       0  505.78      .1       0
Bank Sta=479.37,505.78
XS Rating Curve= 0 ,0
Exp/Cntr=0.3,0.1

Type RM Length L Ch R = 1 ,1602    ,591.4,586.7,581.6
XS GIS Cut Line= 4
2251934.00532507713729.1232096292252128.37877465713455.110877852
2252180.70914273713342.8800022172252261.03915643713039.379128968
#Sta/Elev= 30
       0 2004.87    10.7 2001.18    30.2 1996.86      66 1986.42    93.6 1980.96
   128.2 1976.77   191.2 1963.01   225.5  1960.5   252.6 1957.39   276.9 1947.42
   285.5 1944.82   299.9  1942.3   328.7 1939.79   364.3 1929.58   376.4 1929.48
  381.171928.134     391 1927.28  403.441928.132   415.5 1930.26   427.6 1933.64
   439.6 1934.97   465.7 1940.05     536 1959.91   548.4 1961.23   577.4  1971.4
   589.8 1974.49   631.2 1982.06   726.4 1995.51   748.7 2000.45   773.7 2009.76
#Mann= 3 ,-1,0
       0      .1       0  381.17    .045       0  403.44      .1       0
Bank Sta=381.17,403.44
XS Rating Curve= 0 ,0
Exp/Cntr(USF)=0,0
Exp/Cntr=0.3,0.1

Type RM Length L Ch R = 1 ,1015    ,386.9,388.6,389.5
XS GIS Cut Line= 4
2252718.65422719713840.7981277522252722.15902498713551.862822061
2252692.68677297713452.243825966 2252552.3965698713134.516243542
#Sta/Elev= 30
       0 1979.55    55.6 1971.31   107.6 1957.85   143.6 1945.86   163.6 1940.91
   211.6 1935.33   220.8 1935.14   255.6 1929.88   267.6 1926.47   295.9 1920.94
   312.6 1913.53   318.5 1911.79   329.3 1911.77   341.8 1910.57   354.3 1913.82
   375.2 1915.11   392.8 1924.79   404.9 1928.63   418.1 1931.47   431.2 1932.47
   441.1 1934.74   474.4 1936.37   493.1 1939.09   516.9 1945.86   527.4 1950.18
   544.2 1955.38   584.2 1964.42   621.9 1974.99   667.3 1981.86   740.2 1989.09
#Mann= 3 ,-1,0
       0      .1       0   318.5    .045       0   329.3      .1       0
Bank Sta=318.5,329.3
XS Rating Curve= 0 ,0
Exp/Cntr(USF)=0,0
Exp/Cntr=0.3,0.1

Type RM Length L Ch R = 1 ,627     ,370.5,373.5,375.1
XS GIS Cut Line= 4
2253056.98232337713777.1013756122253100.37918501713546.067948039
 2253090.4784351713409.169070487 2252837.1627507713135.144010865
#Sta/Elev= 30
       0 1974.38    36.6 1968.62    73.2 1961.37   105.7  1950.4   166.8 1937.34
     179 1933.61   199.3 1930.58   219.7 1924.72   258.5 1916.84   272.1 1915.18
   280.1 1912.35   296.1 1904.61  303.981902.929   312.2    1902  322.18 1902.93
   336.2 1906.13   340.2 1906.25   375.7 1904.82   388.1 1905.38   421.3 1904.65
   432.2 1905.41   464.5 1904.05   481.3 1906.47   501.3 1912.02   524.8 1916.41
   594.7  1935.9   611.7 1939.52   655.6 1947.01   671.9 1950.66   745.5    1961
#Mann= 3 ,-1,0
       0      .1       0  303.98    .045       0  322.18      .1       0
#XS Ineff= 2 , 0
                          342.53         1925.21
Permanent Ineff=
       F       F
Bank Sta=303.98,322.18
XS Rating Curve= 0 ,0
Exp/Cntr(USF)=0,0
Exp/Cntr=0.3,0.1

Type RM Length L Ch R = 1 ,253     ,228.1,224.9,224.6
XS GIS Cut Line= 4
2253221.88631192713652.8243732582253245.69048048713334.155665079
2253213.43967146713195.1700357292252982.30887348713140.650810956
#Sta/Elev= 30
       0 1936.54    39.8 1931.29    79.9 1923.73    91.9 1923.29     132 1916.37
   172.1 1905.52   184.2 1905.56   196.2 1903.67   264.4  1902.6   312.5 1899.77
     375 1900.36     385 1899.16  393.941895.413   398.6 1894.14   410.9 1893.03
  416.391895.432   427.3 1902.38   431.4 1903.81   462.2 1909.27   471.8  1911.9
   512.9 1927.47   537.5 1934.46   545.7 1934.89   595.7 1941.59   611.5  1945.7
   623.8 1946.03   640.3 1949.95   648.5    1950   673.1 1953.54   699.7 1955.43
#Mann= 3 ,-1,0
       0      .1       0  393.94    .045       0  416.39      .1       0
Bank Sta=393.94,416.39
XS Rating Curve= 0 ,0
Exp/Cntr(USF)=0,0
Exp/Cntr=0.3,0.1

Type RM Length L Ch R = 1 ,28      ,,,
XS GIS Cut Line= 4
2253323.62234351713667.3064489162253436.99700917713180.818064471
2253380.35497311713044.3886880672253036.52573485713077.253483382
#Sta/Elev= 30
       0 1922.53    78.8 1913.09   100.8 1912.09   141.8 1905.44     150 1903.08
   178.8 1900.34   273.3 1895.08     454 1895.61   481.9 1889.58  533.661885.012
   546.8 1883.49  557.431885.012   574.7 1890.06   594.4  1892.1   603.9 1891.65
   637.3 1893.93   647.4  1893.4   655.5 1890.97   667.5 1894.58   707.7  1894.5
   728.8 1897.94   776.5 1897.56   832.3 1902.46   876.5 1915.99   900.6 1927.37
   916.6 1937.66   924.7 1941.16   960.8 1949.77   976.9  1955.3   992.6  1957.8
#Mann= 7 ,-1,0
       0      .1       0     280     .05       0     320      .1       0
     380     .05       0     480      .1       0  533.66    .045       0
  557.43      .1       0
Bank Sta=533.66,557.43
XS Rating Curve= 0 ,0
Exp/Cntr(USF)=0,0
Exp/Cntr=0.3,0.1
LCMann Table=0

Chan Stop Cuts=-1
Use User Specified Reach Order=0
Composite Channel Slope=5